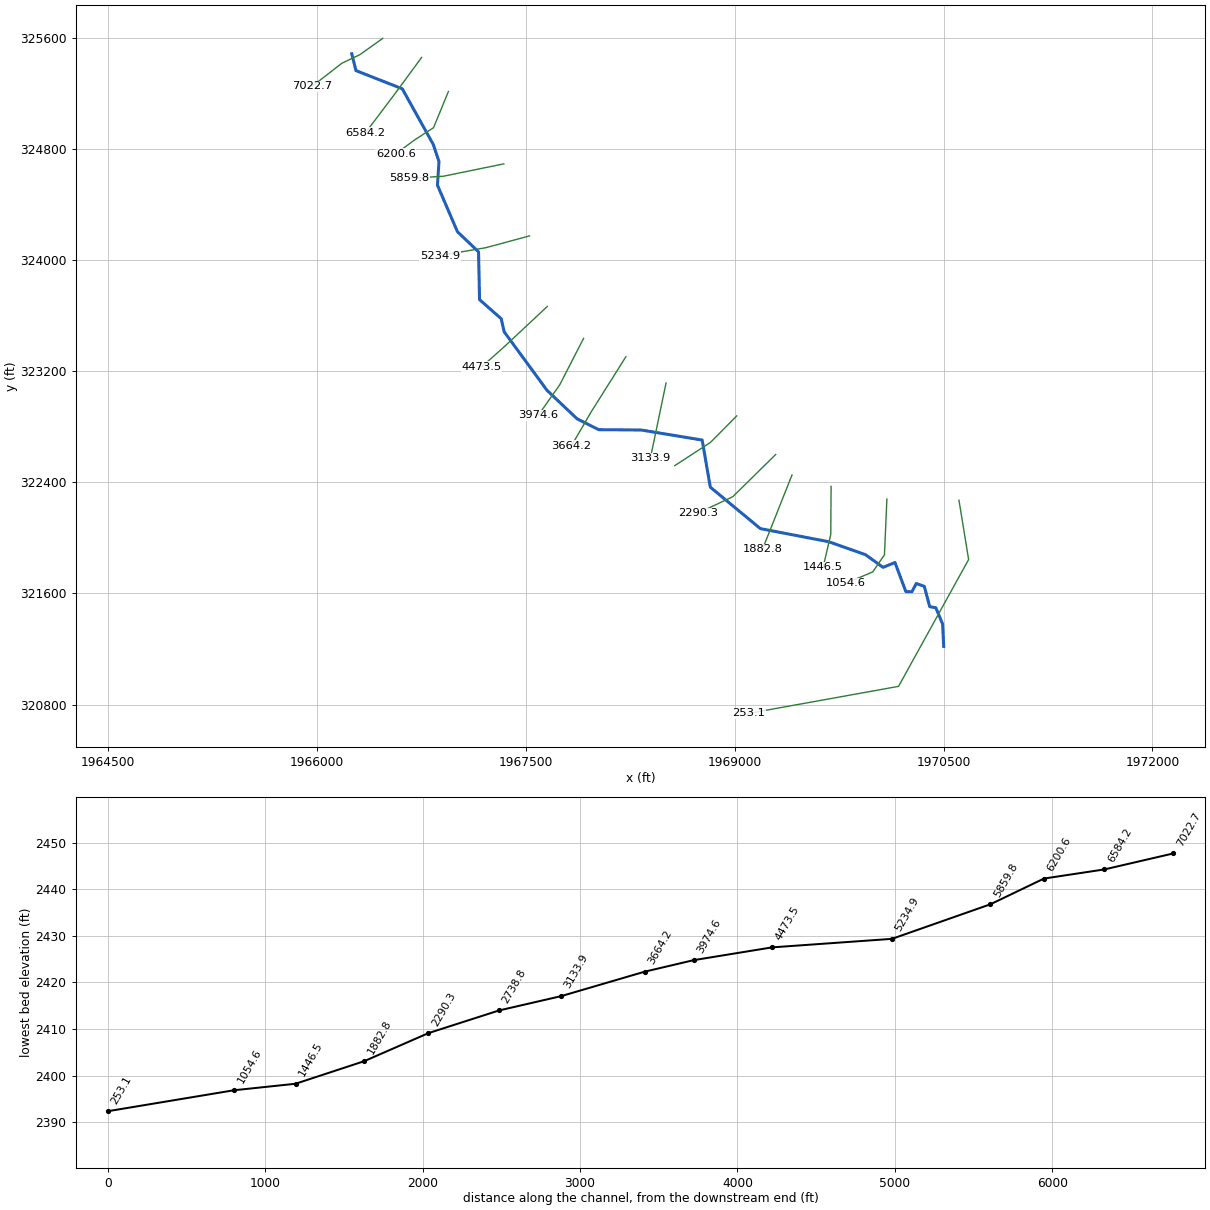
--- NP10.prj (project) ---

Proj Title=NP10
Current Plan=p01
Default Exp/Contr=0,0
English Units
Geom File=g01
Flow File=f01
Plan File=p01
BEGIN DESCRIPTION:
END DESCRIPTION:
DSS Export Rating Curves= 0
DSS Export Rating Curve Sorted= 0
DSS Export Volume Flow Curves= 0
DXF OffsetX= 0
DXF OffsetY= 0
DXF ScaleX= 0
DXF ScaleY= 0

--- NP10.p01 (plan) ---

Plan Title=Floodplain
Program Version=4.00
Geom File=g01
Flow File=f01
K Sum by GR=0
Std Step Tol=0.01
Critical Tol=0.01
Num of Std Step Trials=20
Max Error Tol=0.3
Flow Tol Ratio=0.001
Split Flow NTrial=30
Split Flow Tol=0.02
Split Flow Ratio=0.02
Log Output Level=0
Friction Slope Method=1
Unsteady Friction Slope Method=2
Unsteady Bridges Friction Slope Method=1
Global Log Level=0
CheckData=False
Run HTab=0
Run UNet=0
Run PostProcess=0
UNET Theta=0
UNET Theta Warmup=0
UNET ZTol=0
UNET ZSATol=0
UNET MxIter=0
UNET MaxInSteps=0
UNET DtIC=0
UNET DtMin=0
UNET MaxCRTS=0
UNET WFStab=0
UNET SFStab=0
UNET WFX=0
UNET SFX=0
UNET DSS MLevel=0
UNET DZMax Abort=0
UNET Convert EG Bridges=0
UNET Use Existing IB Tables=0
UNET Froude Limit=0
UNET Froude Power=0
Write IC File=0
Echo Input=False
Echo Output=False
Write Detailed=0

--- NP10.f01 (steady flow) ---

Flow Title=NFF Regression Equation
Program Version=4.10
Number of Profiles= 1
Profile Names=P100yr
River Rch & RM=NP10,Main            ,7022.7
519.7932
River Rch & RM=NP10,Main            ,5859.8
576.9312
River Rch & RM=NP10,Main            ,3133.9
624.5373
River Rch & RM=NP10,Main            ,253.1
677.8582
Boundary for River Rch & Prof#=NP10,Main            , 1
Up Type= 0
Dn Type= 3
Dn Slope=0.0035
DSS Import GetInterval= 0
DSS Import GetPeak= 0
DSS Import FillOption= 0

--- NP10.g01 (geometry) ---

Geom Title=USGS 10m DEM
Program Version=4.10

River Reach=NP10            ,Main
Reach XY= 30
     1966248.399      325484.778     1966278.842      325363.451
     1966611.452      325232.606     1966833.891      324832.216
     1966875.123      324708.518     1966864.273      324538.162
     1967007.502       324203.96     1967159.412      324058.561
     1967166.573      323714.811     1967322.024       323577.51
     1967343.873      323482.389     1967650.876      323062.309
     1967866.734      322857.168     1968022.135      322778.558
     1968327.822      322776.161     1968765.748       322703.96
     1968824.181      322364.725     1969183.934      322066.374
     1969675.782      321971.754      1969939.57      321878.525
     1970065.011      321787.511     1970150.731      321822.233
     1970228.856      321612.815     1970272.259       321611.73
     1970303.726      321671.408     1970361.235      321650.792
     1970400.437       321504.35     1970444.453       321496.49
     1970493.186      321378.589     1970500.779      321218.643

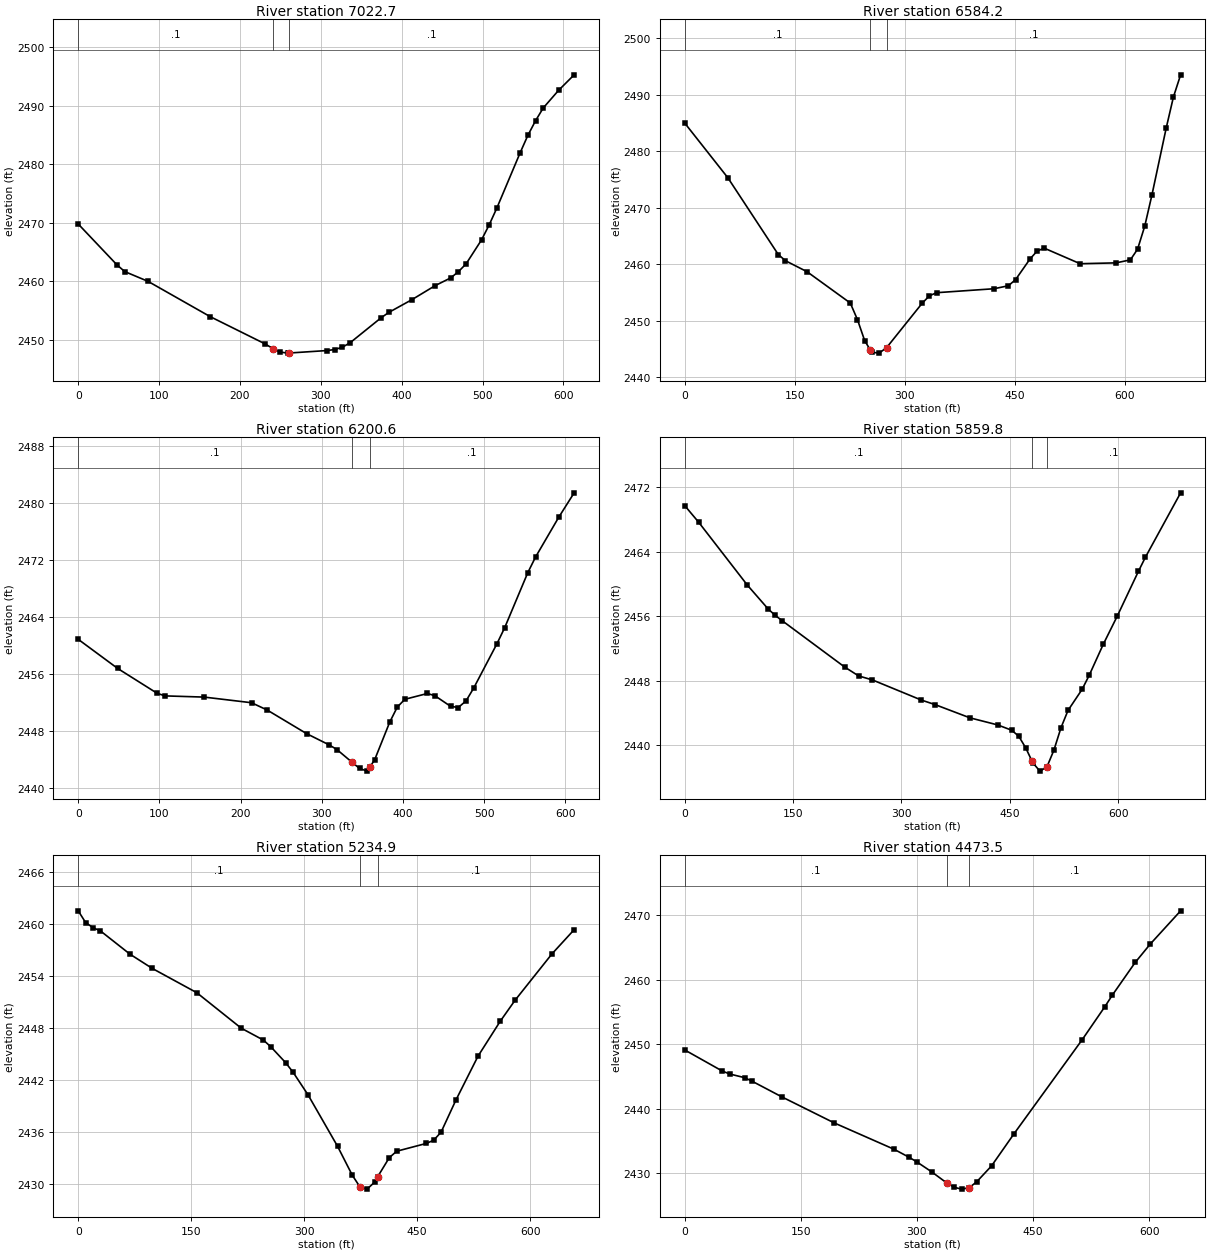
Type RM Length L Ch R = 1 ,7022.7  ,426.4,438.5,449.8
XS GIS Cut Line= 4
     1966471.478      325595.757     1966307.415       325478.57
     1966177.207       325416.07     1965966.269      325252.007
#Sta/Elev= 30
       0  2469.8      48  2462.8    57.6 2461.66    86.4 2459.99   163.2 2453.96
   230.5 2449.34   241.1 2448.48   249.8  2447.9   259.4 2447.72   261.1 2447.74
   307.5 2448.16   317.2 2448.33   326.8 2448.74   336.4 2449.51   374.7 2453.78
   384.2 2454.69   412.9 2456.88   441.5 2459.27   460.6 2460.58   470.1 2461.64
   479.7 2462.99   498.8 2467.09   508.3 2469.68   517.8 2472.56   546.5 2481.98
     556 2484.94   565.6 2487.47   575.1 2489.65   594.2 2492.68   613.3 2495.31
#Mann= 3 , 0 , 0
       0      .1       0   241.1    .045       0   261.1      .1       0
Bank Sta=241.1,261.1
XS Rating Curve= 0 ,0
Exp/Cntr=0.3,0.1

Type RM Length L Ch R = 1 ,6584.2  ,392.5,383.6,374
XS GIS Cut Line= 3
     1966750.558      325458.156     1966553.075      325189.059
     1966346.912      324915.621
#Sta/Elev= 30
       0 2485.02    58.9 2475.32   127.6 2461.74   137.4 2460.64   166.9 2458.69
   225.8 2453.15   235.6  2450.2   245.4  2446.5  253.33 2444.79   255.2 2444.44
   265.1 2444.28   275.3 2445.25     324 2453.14   333.8 2454.44   343.6 2454.98
   421.8 2455.68   441.4 2456.21   451.2  2457.3   470.8 2460.94   480.6 2462.36
   490.3 2462.86   539.2 2460.11   588.2 2460.26   607.7 2460.79   617.5 2462.68
   627.3 2466.77   637.1 2472.29   656.7 2484.22   666.4 2489.63   676.2 2493.55
#Mann= 3 , 0 , 0
       0      .1       0  253.33    .045       0   275.3      .1       0
Bank Sta=253.33,275.3
XS Rating Curve= 0 ,0
Exp/Cntr=0.3,0.1

Type RM Length L Ch R = 1 ,6200.6  ,353.4,340.8,327.7
XS GIS Cut Line= 4
     1966942.832      325212.945     1966836.061      324952.528
     1966703.248      324866.591     1966565.228      324765.028
#Sta/Elev= 30
       0 2460.82    48.5 2456.74      97 2453.26   106.8 2452.88   155.3 2452.71
   213.5 2451.92   232.9 2450.89   281.4 2447.58   309.4 2445.99   318.7 2445.35
   337.3 2443.57   346.6  2442.7   355.9 2442.32   359.2 2442.88   365.2 2443.91
   383.8  2449.2   393.1 2451.31   402.4  2452.4   430.3 2453.22   439.6 2452.89
   458.7 2451.42   468.2 2451.25   477.7 2452.16   487.2 2453.97   515.8 2460.18
   525.3 2462.42   553.9 2470.18   563.4 2472.36     592 2477.95     611 2481.38
#Mann= 3 , 0 , 0
       0      .1       0   337.3    .045       0   359.2      .1       0
Bank Sta=337.3,359.2
XS Rating Curve= 0 ,0
Exp/Cntr=0.3,0.1

Type RM Length L Ch R = 1 ,5859.8  ,622.1,624.9,627.5
XS GIS Cut Line= 3
     1967340.835      324692.097     1966906.808      324603.121
     1966663.752       324587.93
#Sta/Elev= 30
       0 2469.73    19.3 2467.67    86.7 2459.87   115.6  2456.9   125.2 2456.12
   134.8 2455.46   221.5  2449.7   240.8  2448.6     260  2448.1   327.5 2445.61
   346.7 2445.04   394.9  2443.4   433.4 2442.52   452.8 2441.86   462.5 2441.12
   472.3 2439.65   480.6 2438.08     482 2437.82   491.8 2436.79   501.5 2437.31
   511.2  2439.4     521 2442.18   530.7 2444.32   550.2 2446.93     560 2448.67
   579.4  2452.5   598.9 2456.02   628.1 2461.56   637.9 2463.33   686.6 2471.31
#Mann= 3 , 0 , 0
       0      .1       0   480.6    .045       0   501.5      .1       0
Bank Sta=480.6,501.5
XS Rating Curve= 0 ,0
Exp/Cntr=0.3,0.1

Type RM Length L Ch R = 1 ,5234.9  ,745.8,761.5,775.6
XS GIS Cut Line= 3
     1967525.297      324173.434     1967211.929      324088.654
     1966882.936      324032.375
#Sta/Elev= 30
       0 2461.53     9.8 2460.18    19.7 2459.58    29.5 2459.21    68.9 2456.51
    98.4 2454.87   157.4 2452.07   216.4 2447.97   245.9 2446.59   255.8 2445.81
   275.4 2443.98   285.3 2442.87     305 2440.28   344.3 2434.32   363.9 2430.97
   373.7 2429.67   383.5 2429.37   393.4 2430.17   397.4 2430.78     413 2433.01
   422.8 2433.75   462.1 2434.65   471.9 2435.02   481.7 2435.95   501.3 2439.64
   530.8 2444.74   560.2 2448.76   579.9 2451.19     629 2456.56   658.4 2459.35
#Mann= 3 , 0 , 0
       0      .1       0   373.7    .045       0   397.4      .1       0
Bank Sta=373.7,397.4
XS Rating Curve= 0 ,0
Exp/Cntr=0.3,0.1

Type RM Length L Ch R = 1 ,4473.5  ,493.6,498.8,503.7
XS GIS Cut Line= 3
     1967653.335      323665.621     1967343.005      323374.823
     1967182.415      323231.594
#Sta/Elev= 24
       0 2449.13    48.3 2445.87      58  2445.4    77.3 2444.83      87 2444.28
   125.6 2441.84   193.3  2437.8   270.6 2433.71     290 2432.47   299.6 2431.78
     319 2430.22   338.3 2428.51     348 2427.83   357.6 2427.54   367.3 2427.75
     377 2428.66   396.3 2431.14   425.3 2436.12   513.3  2450.7   542.7 2455.84
   552.4 2457.64   581.8 2462.69   601.4 2465.56   640.5  2470.7
#Mann= 3 , 0 , 0
       0      .1       0   338.3    .045       0   367.3      .1       0
Bank Sta=338.3,367.3
XS Rating Curve= 0 ,0
Exp/Cntr=0.3,0.1

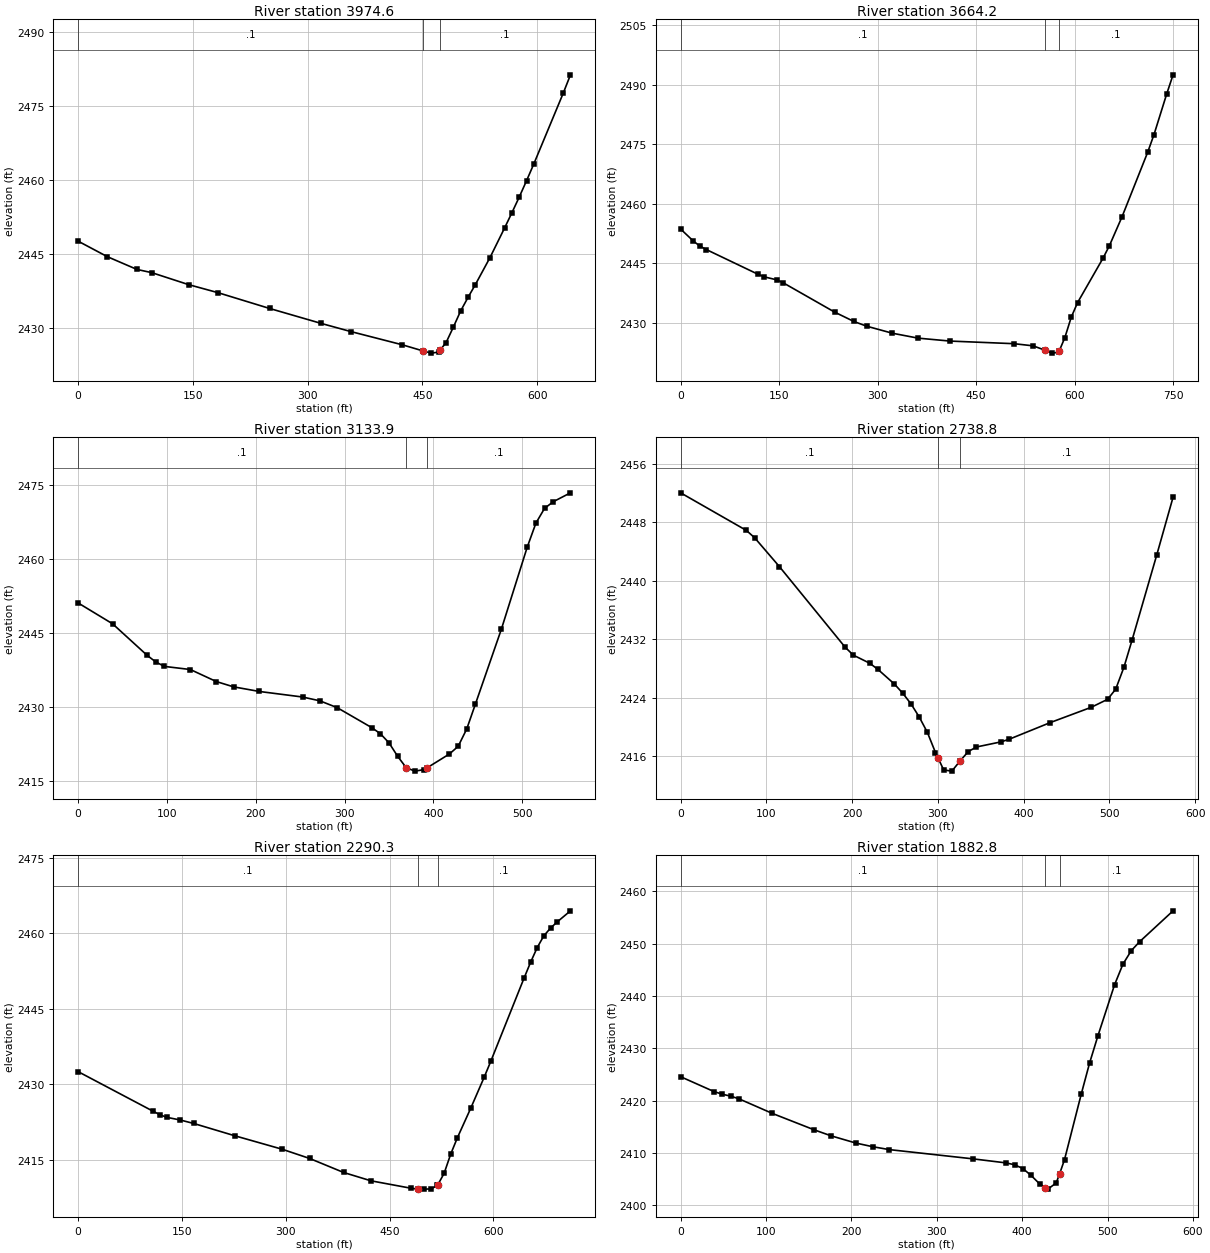
Type RM Length L Ch R = 1 ,3974.6  ,308.2,310.5,312.5
XS GIS Cut Line= 3
     1967913.752      323435.587     1967742.311      323101.385
     1967588.231      322882.201
#Sta/Elev= 27
       0 2447.57    38.5 2444.39      77 2441.81    96.3 2441.16   144.5 2438.72
     183 2437.08   250.4 2433.87   317.8 2430.83   356.4 2429.18   423.4  2426.5
   451.2 2425.22   461.7 2424.79   471.2    2425   472.7 2425.34   480.9 2426.91
   490.4 2430.06     500 2433.37   509.6 2436.12   519.1 2438.69   538.3 2444.21
   557.4 2450.24     567 2453.35   576.6 2456.55   586.1 2459.85   595.7  2463.3
     634 2477.64   643.5 2481.39
#Mann= 3 , 0 , 0
       0      .1       0   451.2    .045       0   472.7      .1       0
Bank Sta=451.2,472.7
XS Rating Curve= 0 ,0
Exp/Cntr=0.3,0.1

Type RM Length L Ch R = 1 ,3664.2  ,521,530.3,538.7
XS GIS Cut Line= 3
     1968217.571      323303.208     1967968.005      322906.073
     1967826.946      322663.017
#Sta/Elev= 30
       0 2453.61    19.5 2450.56    29.3 2449.32    39.1 2448.44   117.3 2442.25
     127 2441.57   146.6 2440.79   156.4 2440.04   234.5 2432.67   263.8 2430.31
   283.4 2429.11   322.5 2427.34   361.6  2426.1   410.4 2425.36   507.8  2424.7
   536.9 2424.16   554.8 2423.07     566 2422.32   575.6 2422.52  576.43 2422.76
   585.3 2426.25     595 2431.38   604.7 2435.08   643.5 2446.29   653.2 2449.44
   672.5 2456.76   711.3 2472.92     721  2477.4   740.4 2487.68   750.1  2492.5
#Mann= 3 , 0 , 0
       0      .1       0   554.8    .045       0  576.43      .1       0
Bank Sta=554.8,576.43
XS Rating Curve= 0 ,0
Exp/Cntr=0.3,0.1

Type RM Length L Ch R = 1 ,3133.9  ,415.5,395,375.3
XS GIS Cut Line= 2
       1968506.2      323114.406     1968393.353      322571.871
#Sta/Elev= 30
       0 2451.08    38.9 2446.85    77.8 2440.47    87.5 2439.14    97.2 2438.24
   126.4 2437.61   155.6 2435.18     175 2434.11   204.2 2433.17   252.8 2432.05
   272.2 2431.28   291.7  2429.9   330.5 2425.87   340.3 2424.63     350 2422.78
   359.7 2420.07   369.4 2417.75   379.2 2417.07   388.9 2417.36   392.5  2417.7
     418 2420.54   427.8 2422.08   437.5 2425.61   447.2 2430.61   476.4 2445.74
   505.5 2462.33   515.3  2467.2     525 2470.18   534.7 2471.52   554.2 2473.33
#Mann= 3 , 0 , 0
       0      .1       0   369.4    .045       0   392.5      .1       0
Bank Sta=369.4,392.5
XS Rating Curve= 0 ,0
Exp/Cntr=0.3,0.1

Type RM Length L Ch R = 1 ,2738.8  ,451.8,448.6,444.1
XS GIS Cut Line= 3
     1969014.012      322877.861      1968825.21      322686.889
     1968569.134      322519.788
#Sta/Elev= 30
       0 2452.02    76.7 2446.88    86.3 2445.88   115.1 2441.95   191.8 2430.93
   201.4 2429.84   220.6 2428.73   230.2 2427.88   249.4 2425.88     259 2424.64
   268.6 2423.19   278.1 2421.42   287.7  2419.3   297.2 2416.53   300.1 2415.81
   306.8 2414.15   316.3 2413.99   325.9 2415.38   335.4 2416.66     345 2417.29
   373.7 2417.99   383.2 2418.35     431 2420.62   478.8 2422.71   497.9  2423.8
   507.4 2425.19     517 2428.19   526.5  2431.9   555.2  2443.5   574.3 2451.42
#Mann= 3 , 0 , 0
       0      .1       0   300.1    .045       0   325.9      .1       0
Bank Sta=300.1,325.9
XS Rating Curve= 0 ,0
Exp/Cntr=0.3,0.1

Type RM Length L Ch R = 1 ,2290.3  ,388.5,407.4,426.5
XS GIS Cut Line= 3
      1969293.96      322600.083     1968985.801      322296.264
     1968734.064      322176.906
#Sta/Elev= 30
       0 2432.47   108.2 2424.61     118 2423.92   127.9 2423.39   147.5 2422.86
   167.2 2422.16   226.2 2419.73     295 2417.04   334.4 2415.22   383.6 2412.43
   422.9 2410.78   480.8  2409.3   490.4 2409.15   499.9 2409.12   509.6 2409.16
   519.2 2409.85   519.9 2410.03   528.8 2412.26   538.4 2416.11     548 2419.34
   567.2 2425.18   586.5  2431.3   596.1 2434.48   644.1 2450.99   653.7 2454.19
   663.3 2457.12   672.9 2459.46   682.5 2460.98   692.1  2462.2   711.3 2464.41
#Mann= 3 , 0 , 0
       0      .1       0   490.4    .045       0   519.9      .1       0
Bank Sta=490.4,519.9
XS Rating Curve= 0 ,0
Exp/Cntr=0.3,0.1

Type RM Length L Ch R = 1 ,1882.8  ,432.2,436.3,439.8
XS GIS Cut Line= 2
     1969411.148      322452.514     1969198.474      321916.489
#Sta/Elev= 30
       0 2424.58    39.1 2421.74    48.9 2421.23    58.6 2420.87    68.4 2420.35
   107.5 2417.56   156.4 2414.43   175.9  2413.3   205.3  2411.9   224.8 2411.21
   244.4 2410.65   342.1 2408.89   381.2 2408.11     391 2407.76   400.7 2407.04
   410.5 2405.71   420.3 2404.12   427.2  2403.4   430.1  2403.1   439.8 2404.28
  443.79    2406   449.6 2408.75   469.2 2421.28   478.9 2427.18   488.7  2432.4
   508.2 2442.16     518 2446.09   527.8 2448.68   537.6 2450.39   576.7 2456.28
#Mann= 3 , 0 , 0
       0      .1       0   427.2    .045       0  443.79      .1       0
Bank Sta=427.2,443.79
XS Rating Curve= 0 ,0
Exp/Cntr=0.3,0.1

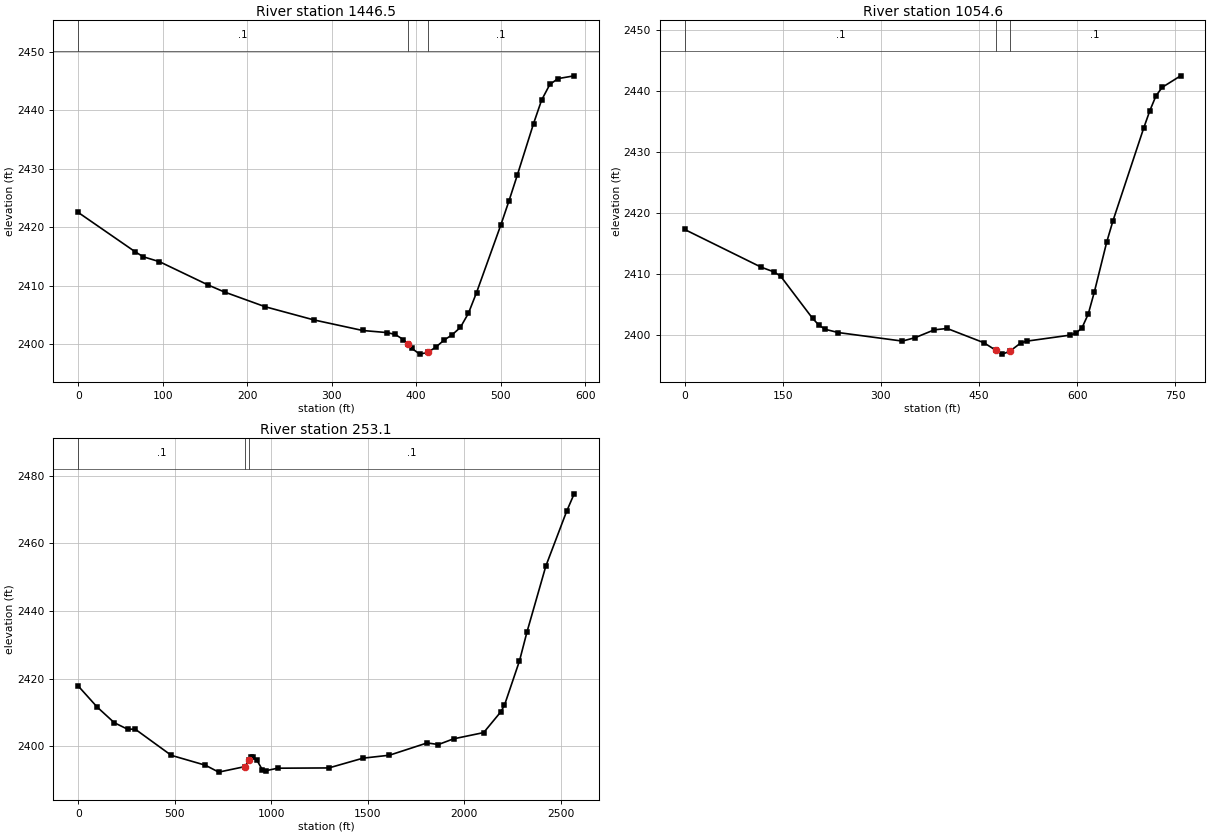
Type RM Length L Ch R = 1 ,1446.5  ,401.2,391.9,382.6
XS GIS Cut Line= 3
     1969691.964      322370.063      1969689.36      322023.709
     1969634.672      321789.334
#Sta/Elev= 30
       0 2422.53    67.4 2415.79      77 2414.93    96.2 2414.09   153.9 2410.09
   173.2 2408.89   221.3 2406.37     279 2404.11   336.7  2402.3   365.6 2401.94
   375.2 2401.62   384.9 2400.74   390.3 2399.92   394.5 2399.28   404.1 2398.25
   413.8 2398.54   423.4 2399.47     433 2400.64   442.6 2401.57   452.3 2402.82
   461.9 2405.26   471.5 2408.81   500.4 2420.46     510 2424.57   519.6 2428.87
   538.9 2437.74   548.5 2441.79   558.2 2444.46   567.8 2445.46     587 2445.94
#Mann= 3 , 0 , 0
       0      .1       0   390.3    .045       0   413.8      .1       0
Bank Sta=390.3,413.8
XS Rating Curve= 0 ,0
Exp/Cntr=0.3,0.1

Type RM Length L Ch R = 1 ,1054.6  ,789.7,801.4,812.9
XS GIS Cut Line= 4
     1970092.571      322278.903      1970075.21       321878.02
     1969990.575      321754.322     1969799.603      321674.027
#Sta/Elev= 30
       0 2417.31   117.4  2411.1     137 2410.33   146.8 2409.63   195.7  2402.7
   205.5 2401.58   215.3 2400.91   234.9 2400.39   332.8 2398.99   352.3 2399.55
   381.7 2400.84   401.3 2401.06   457.5 2398.72   476.2 2397.45   485.6 2396.85
   496.9  2397.3   513.7 2398.67     523 2398.98   588.8 2399.96   598.2 2400.28
   607.6 2401.19   617.1 2403.44   626.5  2407.1   645.3 2415.24   654.7 2418.68
   701.8 2433.94   711.2  2436.8   720.6 2439.24   730.1 2440.64   758.3 2442.53
#Mann= 3 , 0 , 0
       0      .1       0   476.2    .045       0   496.9      .1       0
Bank Sta=476.2,496.9
XS Rating Curve= 0 ,0
Exp/Cntr=0.3,0.1

Type RM Length L Ch R = 1 ,253.1   ,274.3,253.1,228.9
XS GIS Cut Line= 4
     1970610.367       322271.09     1970679.811      321844.007
     1970176.339      320930.812      1969099.95      320736.368
#Sta/Elev= 30
       0 2417.81    98.3 2411.58   186.8 2406.96   255.7 2405.04     295 2405.06
   481.9 2397.32     659 2394.39   727.8 2392.35   865.6 2394.01   885.2 2395.92
   895.1 2396.73   904.9 2396.72   924.6 2395.98   954.1 2393.04   973.8 2392.78
  1032.8 2393.51  1298.4 2393.59  1475.5 2396.48  1612.2 2397.35  1807.5 2400.98
  1866.1 2400.51  1944.3 2402.19  2100.5 2404.04  2188.4 2410.11  2207.9 2412.08
  2286.1 2425.24  2325.1 2433.83  2422.8  2453.3  2530.2 2469.44  2569.3 2474.63
#Mann= 3 , 0 , 0
       0      .1       0   865.6    .045       0   885.2      .1       0
#XS Ineff= 2 , 0
                          894.47          2396.6
Permanent Ineff=
       F       F
Bank Sta=865.6,885.2
XS Rating Curve= 0 ,0
Exp/Cntr=0.3,0.1

Chan Stop Cuts=-1
Use User Specified Reach Order=0
Composite Channel Slope=5